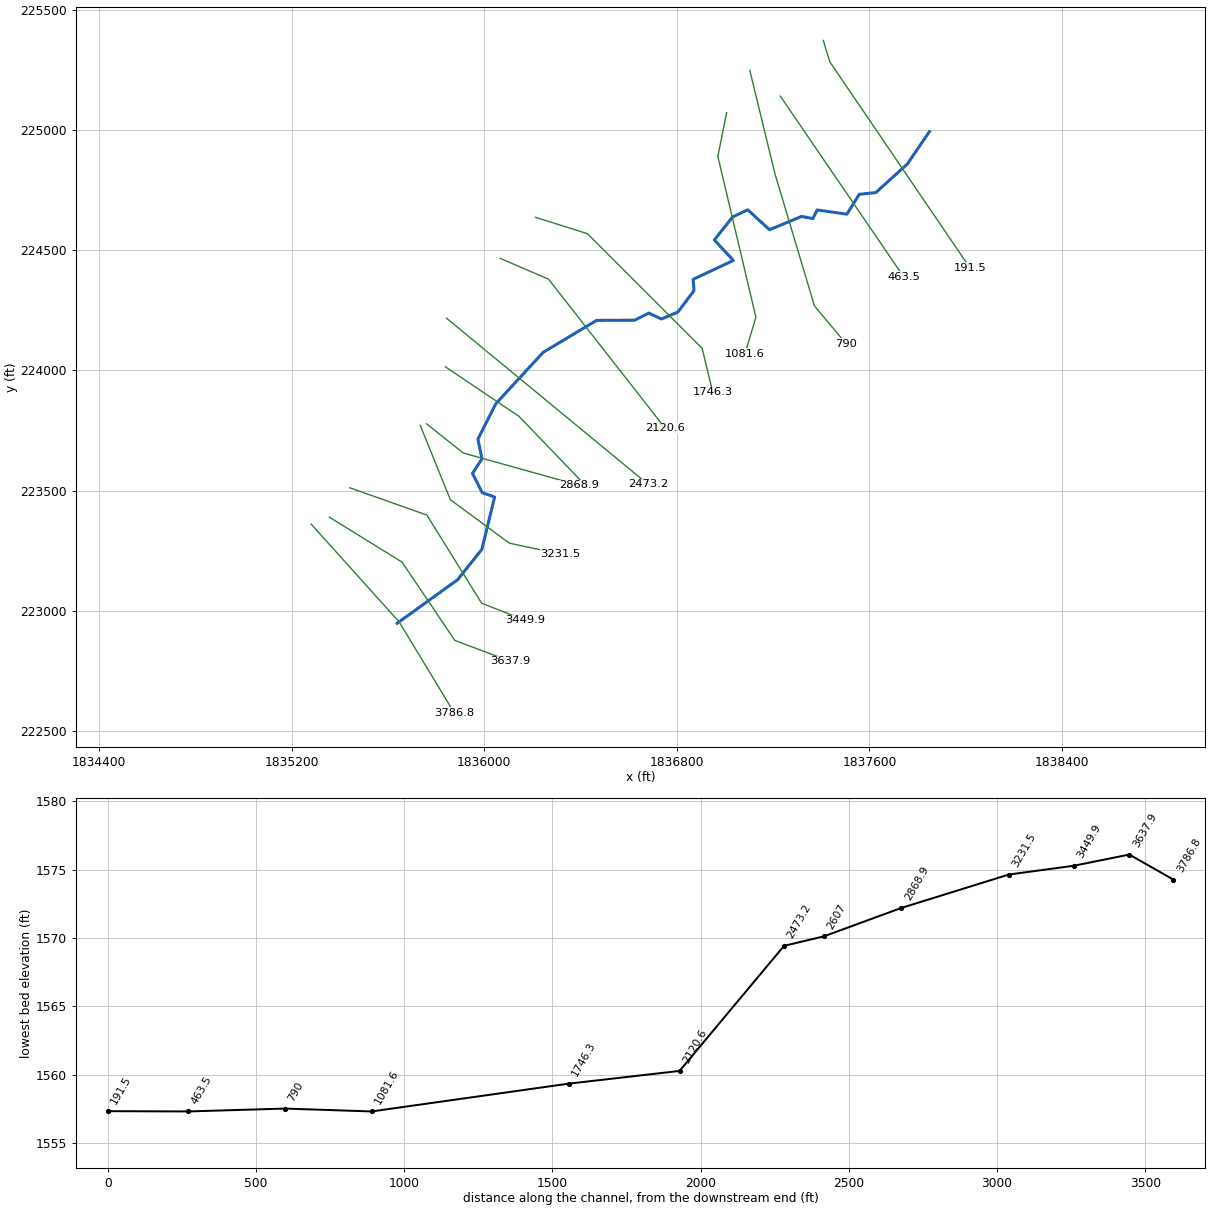
--- WHITMANRN.prj (project) ---

Proj Title=WHITMANRN
Current Plan=p01
Default Exp/Contr=0,0
English Units
Geom File=g01
Flow File=f01
Plan File=p01
BEGIN DESCRIPTION:
END DESCRIPTION:
DSS Export Rating Curves= 0
DSS Export Rating Curve Sorted= 0
DSS Export Volume Flow Curves= 0
DXF OffsetX= 0
DXF OffsetY= 0
DXF ScaleX= 0
DXF ScaleY= 0

--- WHITMANRN.p01 (plan) ---

Plan Title=Floodplain
Program Version=4.00
Geom File=g01
Flow File=f01
K Sum by GR=0
Std Step Tol=0.01
Critical Tol=0.01
Num of Std Step Trials=20
Max Error Tol=0.3
Flow Tol Ratio=0.001
Split Flow NTrial=30
Split Flow Tol=0.02
Split Flow Ratio=0.02
Log Output Level=0
Friction Slope Method=1
Unsteady Friction Slope Method=2
Unsteady Bridges Friction Slope Method=1
Global Log Level=0
CheckData=False
Run HTab=0
Run UNet=0
Run PostProcess=0
UNET Theta=0
UNET Theta Warmup=0
UNET ZTol=0
UNET ZSATol=0
UNET MxIter=0
UNET MaxInSteps=0
UNET DtIC=0
UNET DtMin=0
UNET MaxCRTS=0
UNET WFStab=0
UNET SFStab=0
UNET WFX=0
UNET SFX=0
UNET DSS MLevel=0
UNET DZMax Abort=0
UNET Convert EG Bridges=0
UNET Use Existing IB Tables=0
UNET Froude Limit=0
UNET Froude Power=0
Write IC File=0
Echo Input=False
Echo Output=False
Write Detailed=0

--- WHITMANRN.f01 (steady flow) ---

Flow Title=NFF Regression Equation
Program Version=5.03
Number of Profiles= 1
Profile Names=P100yr
River Rch & RM=WHITMANRN,Main            ,3786.8
614.9839
River Rch & RM=WHITMANRN,Main            ,3449.9
 616.073
River Rch & RM=WHITMANRN,Main            ,2868.9
705.9963
River Rch & RM=WHITMANRN,Main            ,790
741.2179
River Rch & RM=WHITMANRN,Main            ,463.5
742.9943
Boundary for River Rch & Prof#=WHITMANRN,Main            , 1
Up Type= 0
Dn Type= 3
Dn Slope=0.00498
DSS Import GetInterval= 0
DSS Import GetPeak= 0
DSS Import FillOption= 0

--- WHITMANRN.g01 (geometry) ---

Geom Title=USGS 10m DEM
Program Version=4.10

River Reach=WHITMANRN       ,Main
Reach XY= 30
     1835638.542      222949.208     1835889.411      223129.881
     1835990.281      223256.371     1836043.224      223473.924
     1835992.016      223491.882     1835951.289      223571.978
     1835990.691      223632.399     1835973.942      223714.215
     1836047.708      223861.006     1836245.087       224075.56
     1836467.051      224208.133     1836625.228      224208.943
      1836683.08      224238.437     1836736.302      224213.792
     1836804.383      224242.697     1836871.256      224331.705
     1836867.748      224378.703      1837034.65      224457.168
     1836955.644      224542.549     1837031.649      224638.107
     1837094.209      224667.798     1837184.755       224585.04
     1837317.434      224639.928     1837365.292      224631.446
     1837382.506      224667.127     1837506.255      224649.473
     1837557.405      224732.093      1837626.62      224739.535
      1837757.26      224858.312      1837848.98      224992.885

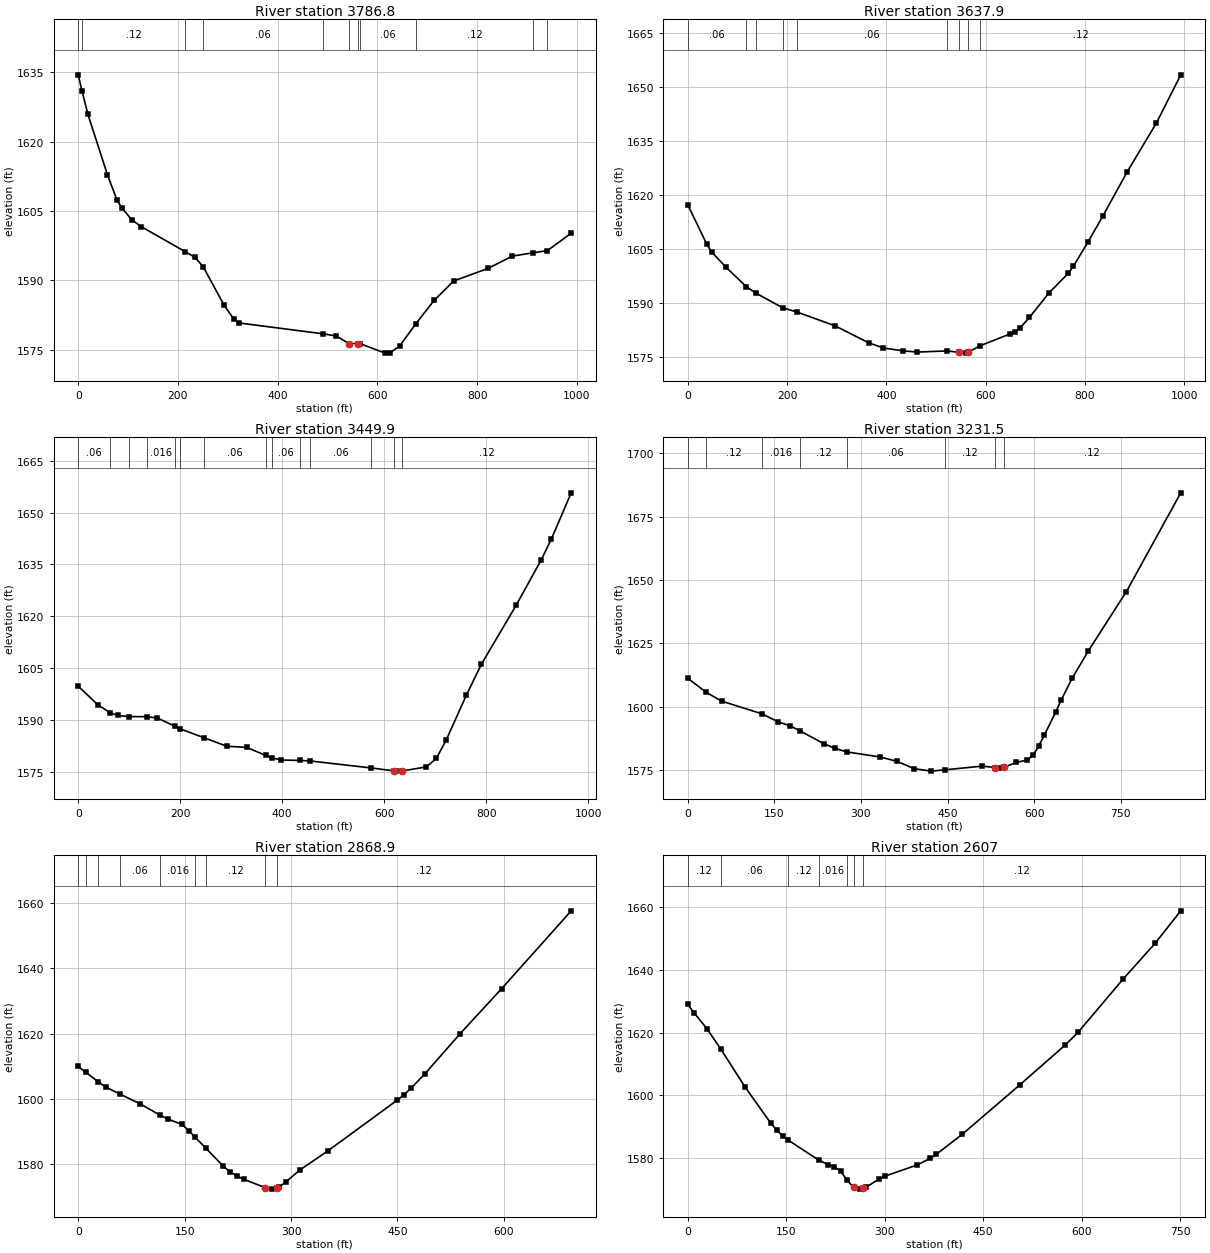
Type RM Length L Ch R = 1 ,3786.8  ,152.1,148.9,150
XS GIS Cut Line= 3
     1835281.513      223360.937     1835647.098      222954.383
     1835875.854      222576.118
#Sta/Elev= 30
       0 1634.46    7.531631.033    19.5 1625.91    58.6 1612.86    78.1  1607.3
    87.9 1605.65   107.4 1603.11   126.9  1601.6  214.261596.236   234.3 1594.98
  250.651592.956   292.9 1584.59   312.4 1581.59   322.2  1580.8  491.921578.438
   517.5 1577.97  542.91 1576.34  560.66 1576.34  564.991576.332   615.5 1574.27
   625.3 1574.32     645 1575.86  677.291580.629   713.8 1585.67     753 1589.86
   821.8 1592.58   870.9 1595.26  912.171595.966  941.16 1596.45   988.8 1600.21
#Mann= 11 ,-1 , 0
       0     .06       0    7.53     .12       0  214.26    .016       0
  250.65     .06       0  491.92     .12       0  542.91    .045       0
  560.66     .12       0  564.99     .06       0  677.29     .12       0
  912.17     .06       0  941.16     .12       0
Bank Sta=542.91,560.66
XS Rating Curve= 0 ,0
Exp/Cntr=0.3,0.1

Type RM Length L Ch R = 1 ,3637.9  ,188.8,188,186.3
XS GIS Cut Line= 4
     1835357.196       223389.96     1835658.846      223203.328
      1835878.03      222877.808     1836108.064      222791.002
#Sta/Elev= 30
       0 1617.27    38.4  1606.3    47.9 1604.21    76.7 1599.97  117.911594.542
  137.211592.757  191.451588.656   219.91587.511   297.2 1583.65   364.5 1578.95
     394 1577.54   433.2 1576.72   462.6  1576.4  522.851576.711  545.45 1576.33
   560.8  1576.1  564.17 1576.31  589.311578.174     649 1581.41   658.8 1582.04
   668.7 1583.01   688.3 1586.02   727.5 1592.78   766.8 1598.31   776.7 1600.18
   806.2 1606.95   835.7 1614.05   884.8 1626.33   943.8 1639.93     993 1653.33
#Mann= 9 ,-1 , 0
       0     .06       0  117.91    .016       0  137.21     .06       0
  191.45    .016       0   219.9     .06       0  522.85     .12       0
  545.45    .045       0  564.17     .06       0  589.31     .12       0
Bank Sta=545.45,564.17
XS Rating Curve= 0 ,0
Exp/Cntr=0.3,0.1

Type RM Length L Ch R = 1 ,3449.9  ,209.7,218.4,227.1
XS GIS Cut Line= 4
     1835441.845      223512.298     1835762.041      223398.811
     1835989.211      223032.579     1836171.503      222960.964
#Sta/Elev= 30
       0 1599.82    38.8 1594.41   62.071592.201    77.6 1591.37   98.921591.038
  134.121591.008   155.3 1590.64  189.311588.265  199.541587.509  246.991584.911
   291.2 1582.48     330 1582.14  367.881579.828  380.741579.067   398.5 1578.49
   434.31578.377  454.481578.225  573.751576.207   619.3 1575.35   623.8 1575.28
   634.3 1575.31   682.5  1576.5   702.1 1578.93   721.7 1584.34   760.9  1597.2
   790.3 1606.13   858.8 1623.26   907.8 1636.34   927.4 1642.27   966.5  1655.7
#Mann= 14 ,-1 , 0
       0     .06       0   62.07     .12       0   98.92     .06       0
  134.12    .016       0  189.31     .06       0  199.54    .016       0
  246.99     .06       0  367.88     .12       0  380.74     .06       0
   434.3     .12       0  454.48     .06       0  573.75     .12       0
   619.3    .045       0   634.3     .12       0
Bank Sta=619.3,634.3
XS Rating Curve= 0 ,0
Exp/Cntr=0.3,0.1

Type RM Length L Ch R = 1 ,3231.5  ,352.6,362.6,370.1
XS GIS Cut Line= 4
     1835734.437      223771.728     1835859.437        223462.7
     1836104.229      223282.144     1836316.034      223237.006
#Sta/Elev= 30
       0  1611.3   31.671605.761    58.8 1602.24  127.911597.304   156.9 1594.04
   176.5  1592.6  195.211590.447   235.3 1585.52   254.9 1583.64  275.831582.208
   333.4 1580.22   362.8 1578.47   392.2 1575.61   421.7 1574.64  446.051575.167
     510 1576.61   532.8 1576.07   539.4 1575.79   547.8 1576.13   568.8 1578.05
   588.5 1579.07   598.3 1580.93   608.1 1584.53   617.9 1588.91   637.5 1597.97
   646.9  1602.7   665.8 1611.21     694 1622.08   759.9 1645.47   854.1 1684.44
#Mann= 8 ,-1 , 0
       0     .06       0   31.67     .12       0  127.91    .016       0
  195.21     .12       0  275.83     .06       0  446.05     .12       0
   532.8    .045       0   547.8     .12       0
Bank Sta=532.8,547.8
XS Rating Curve= 0 ,0
Exp/Cntr=0.3,0.1

Type RM Length L Ch R = 1 ,2868.9  ,269.3,261.9,253.7
XS GIS Cut Line= 3
     1835760.479      223778.238     1835912.752      223656.887
     1836394.523      223522.339
#Sta/Elev= 30
       0 1609.87   10.761608.085   28.591605.103    38.9 1603.55   59.161601.357
    87.6 1598.37  115.931594.838   126.6  1593.7     146 1592.11   155.8 1590.19
  164.591588.196   179.81584.806   204.5 1579.26   214.3 1577.48   224.1 1576.18
   233.9 1575.17   263.4 1572.68   273.2  1572.2  280.22 1572.63     283 1572.78
   292.8 1574.43   312.4 1578.08   351.6 1583.89   449.7 1599.53   459.5 1601.24
   469.3 1603.21     489 1607.69     538 1619.86   596.8 1633.76   694.9 1657.68
#Mann= 9 ,-1 , 0
       0    .016       0   10.76     .06       0   28.59     .12       0
   59.16     .06       0  115.93    .016       0  164.59     .06       0
   179.8     .12       0   263.4    .045       0  280.22     .12       0
Bank Sta=263.4,280.22
XS Rating Curve= 0 ,0
Exp/Cntr=0.3,0.1

Type RM Length L Ch R = 1 ,2607    ,136,133.9,131.6
XS GIS Cut Line= 3
     1835838.967       224014.96     1836144.957      223808.797
     1836409.714      223533.189
#Sta/Elev= 30
       0 1629.12     9.7 1626.33    29.1 1621.37   50.611614.717    87.4 1602.69
   126.2 1591.25   135.9 1588.83   145.6 1586.92  153.43 1585.69  199.481579.391
   213.6 1577.95   223.3 1577.28     233 1575.83  242.311573.066   252.6 1570.69
   262.2 1570.12   267.6 1570.47   271.9 1570.75   291.3 1573.34     301  1574.3
   349.5 1577.83     369  1579.9   378.8 1581.25     418 1587.58   506.2 1603.45
   574.8 1616.06   594.4 1620.11   662.9 1637.06   711.9 1648.53   751.1 1658.93
#Mann= 7 ,-1 , 0
       0     .12       0   50.61     .06       0  153.43     .12       0
  199.48    .016       0  242.31     .12       0   252.6    .045       0
   267.6     .12       0
Bank Sta=252.6,267.6
XS Rating Curve= 0 ,0
Exp/Cntr=0.3,0.1

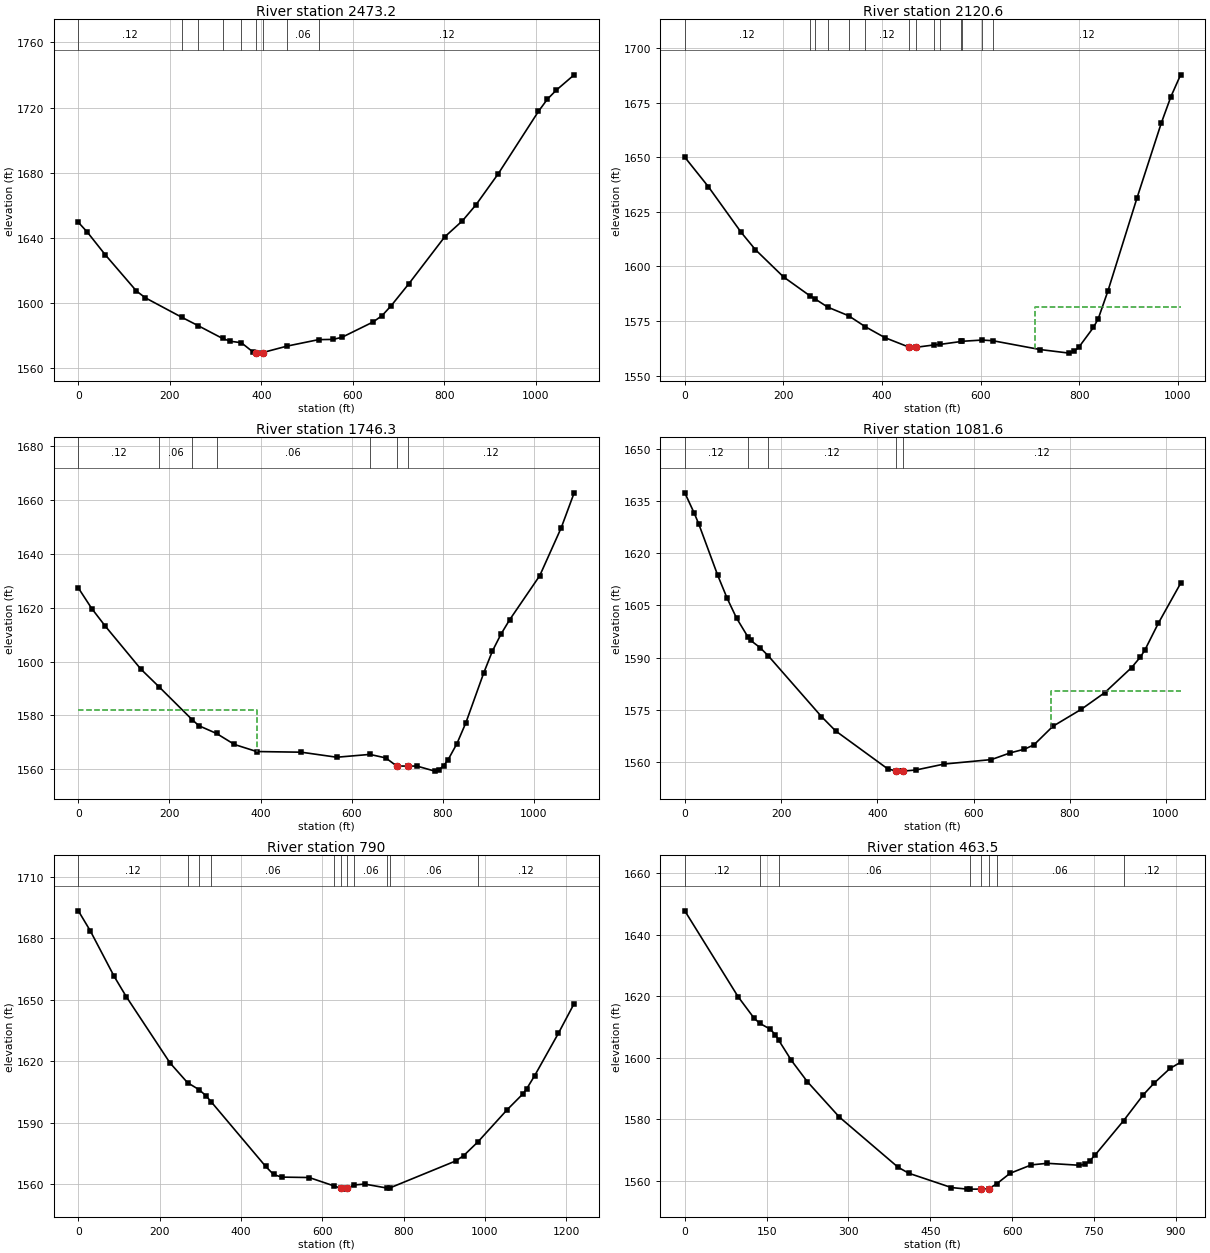
Type RM Length L Ch R = 1 ,2473.2  ,357.5,352.6,347.7
XS GIS Cut Line= 2
     1835843.323       224217.31     1836679.532      223527.544
#Sta/Elev= 30
       0 1649.68    19.5 1643.71    58.6 1629.86     127 1607.54   146.5 1603.37
  226.111591.429  261.961586.266  315.271578.441     332 1576.72  356.341575.815
   380.9 1570.35  388.02 1569.62   390.6 1569.43   402.9 1569.76  456.851573.772
  525.371577.712   556.6 1577.84   576.2 1579.12   644.5 1588.55   664.1 1592.45
   683.6 1598.41   722.7 1612.02   800.8 1640.69   839.8 1650.62   869.1 1660.32
     918 1679.46  1005.9 1717.72  1025.4  1725.2  1044.9 1730.74    1084 1740.16
#Mann= 9 ,-1 , 0
       0     .12       0  226.11     .06       0  261.96     .12       0
  315.27    .016       0  356.34     .12       0  388.02    .045       0
   402.9     .12       0  456.85     .06       0  525.37     .12       0
Bank Sta=388.02,402.9
XS Rating Curve= 0 ,0
Exp/Cntr=0.3,0.1

Type RM Length L Ch R = 1 ,2120.6  ,371.7,374.3,376.3
XS GIS Cut Line= 3
     1836065.774      224466.129     1836267.163      224379.323
     1836751.364      223760.009
#Sta/Elev= 30
       0 1650.09    47.7 1636.59   114.4 1615.61     143 1607.75   200.2 1595.21
  253.251586.631  263.991585.162  289.761581.379  332.041577.434  365.741572.434
     406 1567.36   454.2 1563.08   469.2 1562.97  504.961564.033   517.71564.293
  560.711565.636  563.051565.724  602.771566.277  624.461565.982   720.5 1561.93
   779.4 1560.29   789.2 1561.09   799.1 1563.04   828.6 1572.06   838.4 1576.07
     858 1588.79     917 1631.45   966.1 1665.67   985.8  1677.9  1005.4 1687.84
#Mann= 14 ,-1 , 0
       0     .12       0  253.25     .06       0  263.99     .12       0
  289.76    .016       0  332.04     .06       0  365.74     .12       0
   454.2    .045       0   469.2     .12       0  504.96     .06       0
   517.7     .12       0  560.71     .06       0  563.05     .12       0
  602.77     .06       0  624.46     .12       0
#XS Ineff= 2 , 0
       0                  710.84       0 1581.28
Permanent Ineff=
       F       F
Bank Sta=454.2,469.2
XS Rating Curve= 0 ,0
Exp/Cntr=0.3,0.1

Type RM Length L Ch R = 1 ,1746.3  ,662.3,664.7,649.8
XS GIS Cut Line= 4
     1836213.604      224636.311     1836428.621      224568.559
      1836905.01       224092.04     1836949.281      223908.447
#Sta/Elev= 30
       0 1627.27    29.4 1619.64    58.8 1613.18   137.2 1597.18  177.51 1590.55
  249.771578.438   264.5  1576.2   303.31573.317   342.6 1569.24   391.4 1566.62
   489.1 1566.38   567.2 1564.51  639.771565.559   674.6 1564.26   698.6 1561.26
   723.5 1561.22     743 1561.24   782.1 1559.36   791.8 1559.89   801.6 1561.38
   811.4 1563.57   830.9 1569.58   850.4 1577.26   889.5 1595.69   908.7 1603.87
   927.6 1610.16   946.5 1615.46  1012.6 1631.82  1059.8 1649.61  1088.1 1662.53
#Mann= 7 ,-1 , 0
       0     .12       0  177.51     .06       0  249.77    .016       0
   303.3     .06       0  639.77     .12       0   698.6    .045       0
   723.5     .12       0
#XS Ineff= 2 , 0
          391.33 1581.86
Permanent Ineff=
       F       F
Bank Sta=698.6,723.5
XS Rating Curve= 0 ,0
Exp/Cntr=0.3,0.1

Type RM Length L Ch R = 1 ,1081.6  ,289.6,291.6,292.4
XS GIS Cut Line= 4
     1837006.746      225072.032     1836970.288       224889.74
     1837128.274      224221.337     1837083.135      224070.296
#Sta/Elev= 30
       0 1637.37    19.6 1631.53    29.4 1628.27    68.5 1613.62    88.1 1607.01
   107.6 1601.33  130.711596.033     137 1594.91   156.6 1592.83  173.661590.461
     284 1573.02   313.4  1568.9   421.4 1558.01   438.6 1557.37   450.8 1557.33
   453.6 1557.34   480.2 1557.65   539.1 1559.37   637.2 1560.65   676.5 1562.59
   705.9 1563.64   725.6 1564.89   764.8 1570.21   823.7 1575.09   872.7  1579.9
   928.4  1587.1   946.9 1590.16   956.2 1592.18     984 1599.84  1030.4 1611.35
#Mann= 5 ,-1 , 0
       0     .12       0  130.71    .016       0  173.66     .12       0
   438.6    .045       0   453.6     .12       0
#XS Ineff= 2 , 0
                          761.61         1580.37
Permanent Ineff=
       F       F
Bank Sta=438.6,453.6
XS Rating Curve= 0 ,0
Exp/Cntr=0.3,0.1

Type RM Length L Ch R = 1 ,790     ,321.2,326.5,327.9
XS GIS Cut Line= 4
     1837102.926      225247.422     1837207.093      224818.603
     1837371.329      224268.212     1837502.232      224112.006
#Sta/Elev= 30
       0 1693.36    29.4  1683.6    88.3 1661.31   117.7 1651.54   225.6  1619.1
  268.641609.476   296.41606.152   313.8 1603.17  326.92 1600.12   460.8 1568.61
   480.2 1564.68   499.7 1563.41   567.8  1563.2  628.511559.132   645.7 1557.93
   655.5 1557.54  661.48 1557.89  677.461559.543   704.1 1560.01     7601558.033
  765.861558.101     928 1571.28   947.5 1573.85  982.62 1580.56  1054.5 1596.25
  1093.3 1603.98    1103  1606.6  1122.4 1612.93  1180.6 1633.55  1219.5 1648.11
#Mann= 11 ,-1 , 0
       0     .12       0  268.64    .016       0   296.4     .12       0
  326.92     .06       0  628.51     .12       0   645.7    .045       0
  661.48     .12       0  677.46     .06       0     760     .12       0
  765.86     .06       0  982.62     .12       0
Bank Sta=645.7,661.48
XS Rating Curve= 0 ,0
Exp/Cntr=0.3,0.1

Type RM Length L Ch R = 1 ,463.5   ,269.7,271.9,270.6
XS GIS Cut Line= 2
     1837229.663      225140.217     1837741.815      224389.349
#Sta/Elev= 30
       0 1647.79    97.7 1619.87     127  1612.9   137.3 1611.23   156.4 1609.34
   166.1  1607.5  171.861605.813   195.5 1599.14   224.8 1592.22   283.4 1580.74
   390.9 1564.45   410.5  1562.5   488.7 1557.84     518 1557.33  522.05 1557.33
   542.3 1557.33   557.3 1557.48  571.471559.022   596.2 1562.47   635.2 1565.21
   664.6 1565.72   723.2 1565.09     733 1565.37   742.8 1566.58   752.5  1568.5
  804.311579.575   840.5 1587.99     860 1591.74   889.4 1596.55   908.9 1598.57
#Mann= 8 ,-1 , 0
       0     .12       0   137.3    .016       0  171.86     .06       0
  522.05     .12       0   542.3    .045       0   557.3     .12       0
  571.47     .06       0  804.31     .12       0
Bank Sta=542.3,557.3
XS Rating Curve= 0 ,0
Exp/Cntr=0.3,0.1

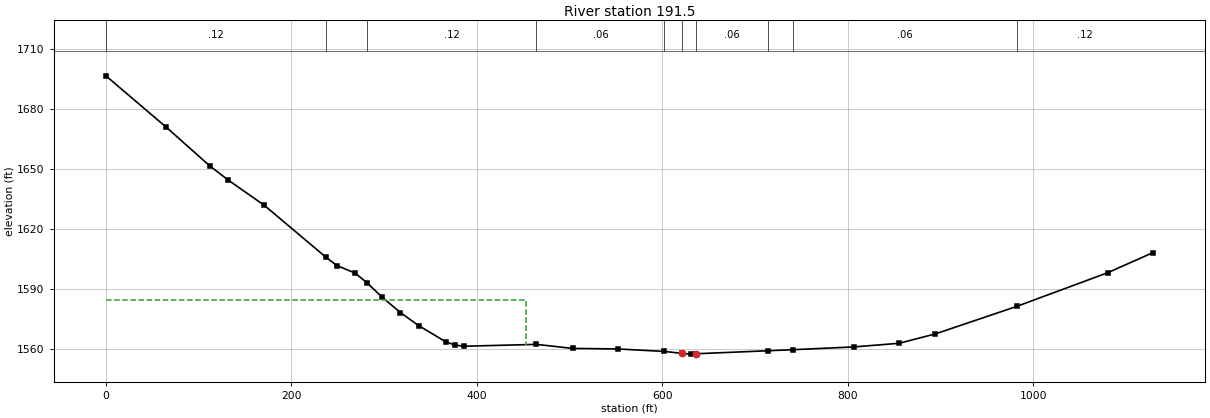
Type RM Length L Ch R = 1 ,191.5   ,185.1,191.5,198.1
XS GIS Cut Line= 3
     1837408.134      225371.831     1837435.044      225283.186
     1838017.457      224425.874
#Sta/Elev= 30
       0 1696.68    64.8 1671.07   112.2  1651.5   131.8 1644.52   170.9 1631.81
  237.191605.888   249.1 1601.68   268.6 1597.95  281.511593.089     298 1585.82
   317.5 1578.17   337.1 1571.67   366.4 1563.55   376.2 1561.92     386  1561.3
   464.11562.231   503.3 1560.21   552.2 1559.93   602.21558.696   620.8 1557.74
   630.4 1557.35   635.8 1557.53  713.451559.034   740.61559.564   806.4 1560.95
   855.3 1562.78   894.4 1567.48  982.031581.232  1080.2 1598.11  1129.1  1608.2
#Mann= 10 ,-1 , 0
       0     .12       0  237.19    .016       0  281.51     .12       0
   464.1     .06       0   602.2     .12       0   620.8    .045       0
   635.8     .06       0  713.45     .12       0   740.6     .06       0
  982.03     .12       0
#XS Ineff= 2 , 0
          453.25 1584.32
Permanent Ineff=
       F       F
Bank Sta=620.8,635.8
XS Rating Curve= 0 ,0
Exp/Cntr=0.3,0.1

Chan Stop Cuts=-1
Use User Specified Reach Order=0
Composite Channel Slope=5